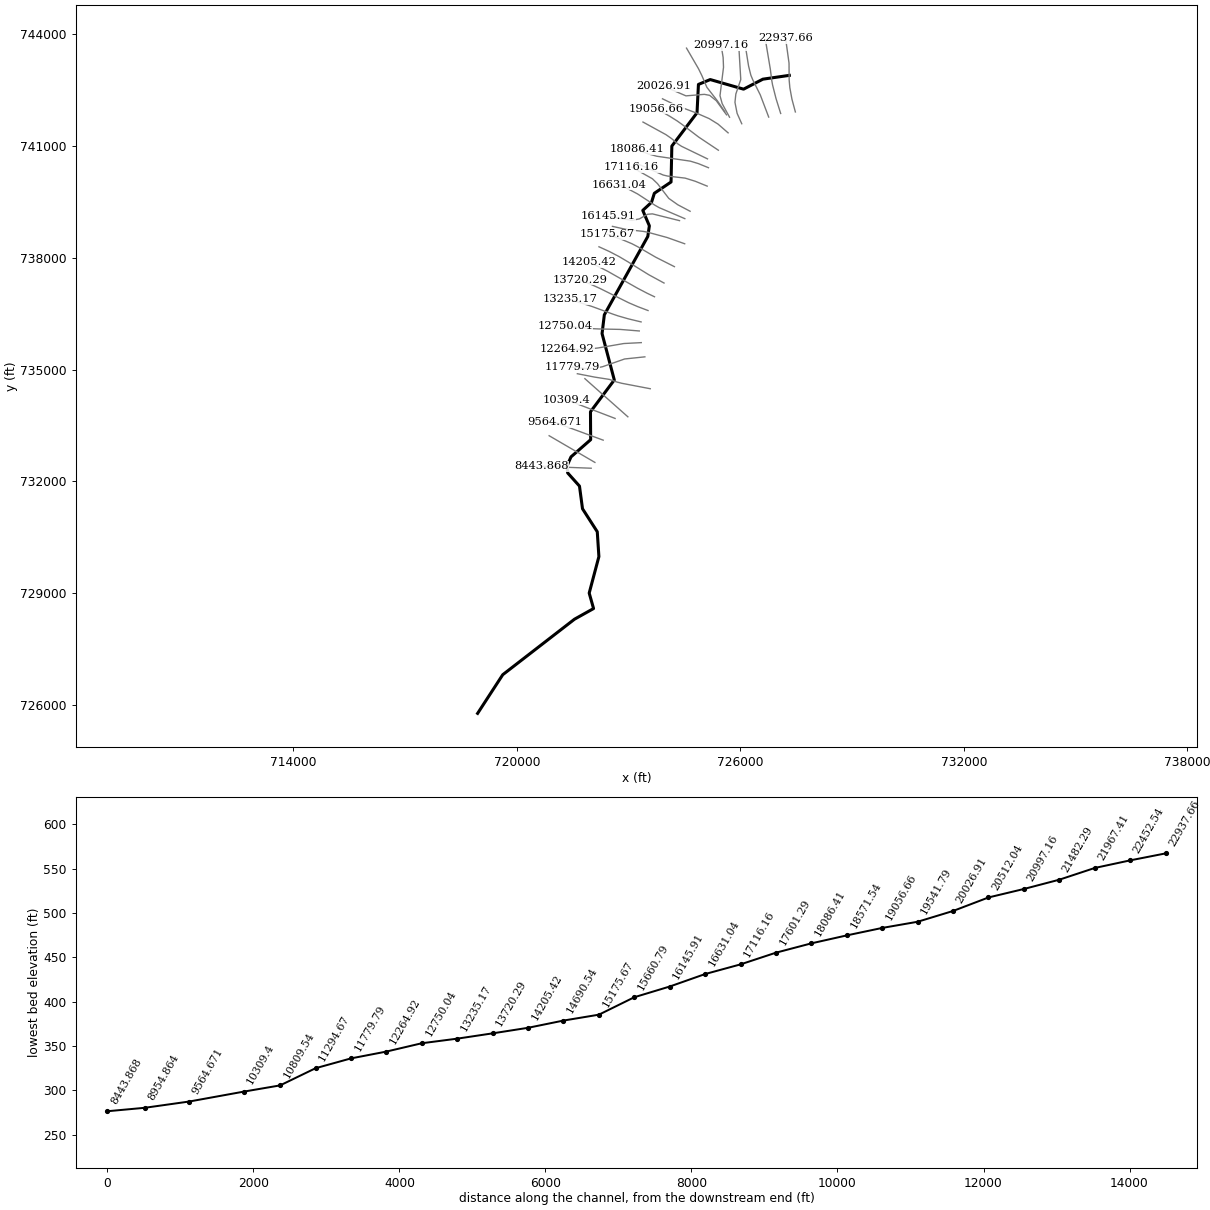
--- 4878_ras.prj (project) ---

Proj Title=4878
Current Plan=p01
Default Exp/Contr=0.3,0.1
English Units
Geom File=g01
Flow File=f01
Plan File=p01
Y Axis Title=Elevation
X Axis Title(PF)=Main Channel Distance
X Axis Title(XS)=Station
BEGIN DESCRIPTION:
RFD model 4878 exported to HEC-RAS
END DESCRIPTION:

--- 4878_ras.p01 (plan) ---

Plan Title=Plan 01
Program Version=4.10
Short Identifier=Plan 01
Geom File=g01
Flow File=f01
Subcritical Flow
Calc Critical at every XS
Secant Critical Depth

--- 4878_ras.f01 (steady flow) ---

Flow Title=Flow 01
Program Version=5.01
Number of Profiles= 6
Profile Names=10yr,25yr,50yr,100yr,100plus,500yr
River Rch & RM=4878,43,22937.66
 3698.16 5825.03  7578.7 9453.7716298.1114026.72
River Rch & RM=4878,43,22452.54
 3718.04 5864.02 7637.13 9536.0516439.9714181.05
River Rch & RM=4878,43,21967.41
 3745.09 5917.13 7716.83  9648.416633.6614392.34
River Rch & RM=4878,43,21482.29
 3756.48 5939.54 7750.48 9695.8916715.5314481.84
River Rch & RM=4878,43,20997.16
 3764.47 5955.26 7774.09 9729.23   1677314544.75
River Rch & RM=4878,43,20512.04
 4023.34 6468.93 8551.0210833.1418676.1216658.74
River Rch & RM=4878,43,20026.91
 4676.43 7800.1710606.8513814.2723815.5222643.67
River Rch & RM=4878,43,19541.79
 4691.94 7832.3610657.2613888.3623943.2522797.13
River Rch & RM=4878,43,19056.66
 4704.69 7858.8510698.7713949.4124048.5122923.74
River Rch & RM=4878,43,18571.54
 4715.61 7881.5510734.3514001.7724138.7723032.44
River Rch & RM=4878,43,18086.41
 4734.87 7921.6310797.2214094.3324298.3423224.86
River Rch & RM=4878,43,17601.29
 4818.47 8095.9911071.2914498.6424995.3724069.24
River Rch & RM=4878,43,17116.16
  4830.9 8121.9811112.2314559.1525099.6824196.14
River Rch & RM=4878,43,16631.04
 4844.22 8149.8511156.1414624.0825211.6224332.47
River Rch & RM=4878,43,16145.91
 5893.3210400.7314772.4620074.8534608.6436300.23
River Rch & RM=4878,43,15660.79
 5899.2910413.8414793.9120107.7334665.3336375.33
River Rch & RM=4878,43,15175.67
 6454.7511647.3916828.9223255.0940091.3143706.97
River Rch & RM=4878,43,14690.54
 6463.21 11666.416860.5523304.4140176.3443824.05
River Rch & RM=4878,43,14205.42
 6555.2611873.4617205.5423843.1341105.0945107.09
River Rch & RM=4878,43,13720.29
 6658.9412107.5317596.6124455.4842160.7746574.76
River Rch & RM=4878,43,13235.17
 6672.3412137.8617647.3724535.0942298.0146766.28
River Rch & RM=4878,43,12750.04
 6842.9612525.1818297.2525556.9344059.6449238.92
River Rch & RM=4878,43,12264.92
 6867.4312580.9318391.0625704.8144314.5949598.95
River Rch & RM=4878,43,11779.79
 6876.6212601.8818426.3125760.4144410.4549734.46
River Rch & RM=4878,43,11294.67
 6941.2612749.42 18674.926152.8845087.0550693.12
River Rch & RM=4878,43,10809.54
  6948.412765.72 18702.426196.3345161.9550799.47
River Rch & RM=4878,43, 10309.4
 6992.68   1286718873.3426466.6445627.9651462.23
River Rch & RM=4878,43,9564.671
 7157.6313245.6919514.24 27482.947379.9853969.79
River Rch & RM=4878,43,8954.864
 7230.3713413.3619798.9227935.6948160.5755094.93
River Rch & RM=4878,43,8443.868
 7245.46 13448.219858.1328029.9748323.1255329.84
River Rch & RM=4878,43,7772.434
 7269.0613502.7219950.8528177.6848577.7655698.23
River Rch & RM=4878,43,7385.471
 7289.1413549.1320029.8128303.5448794.7556012.56
River Rch & RM=4878,43,6998.508
 7292.7913557.5620044.1728326.4448834.2156069.77
River Rch & RM=4878,43,6611.545
 7296.1313565.2920057.3328347.4248870.3956122.23
River Rch & RM=4878,43,6224.583
 7344.3813676.9920247.5828650.9849393.7356882.16
River Rch & RM=4878,43,5734.416
 7429.3313874.0820583.8729188.4650320.3358232.83
River Rch & RM=4878,43,5485.093
 7432.3513881.0820595.8429207.6250353.3558281.08
River Rch & RM=4878,43,4933.378
 7456.3113936.7720690.9929359.9250615.9258665.08
River Rch & RM=4878,43,4192.219
 7461.4313948.6820711.34 29392.550672.0958747.29
Boundary for River Rch & Prof#=4878,43,1
Up Type= 0
Dn Type= 2
Boundary for River Rch & Prof#=4878,43,2
Up Type= 0
Dn Type= 2
Boundary for River Rch & Prof#=4878,43,2
Up Type= 0
Dn Type= 2
Boundary for River Rch & Prof#=4878,43,2
Up Type= 0
Dn Type= 2
Boundary for River Rch & Prof#=4878,43,2
Up Type= 0
Dn Type= 2
Boundary for River Rch & Prof#=4878,43,2
Up Type= 0
Dn Type= 2

--- 4878_ras.g01 (geometry) ---

Geom Title=4878
Program Version=4.10

River Reach=4878,43
Reach XY= 30
727312.817739606742898.177145958726603.312432379742795.983661085
726084.562432379742527.754494429725189.770765692742785.566994429
724873.104099035742654.837827757724835.083265662741893.900327787
724159.041599005  740999.1086611724137.687432379740035.566994429
723689.249932349739732.441994444723613.729099005739490.254494444
723378.833265692739273.066994429723555.395765662738859.525327772
723513.729099005738573.587827772722346.541599005736468.900327772
722285.604099035735965.254494444722614.249932379734720.462827757
721974.666599005733866.296161085721979.354099035733117.337827772
721452.270765662732655.879494444721342.374932349732409.004494429
721363.208265692  732224.1086611721679.354099035731871.504494429
721760.604099035731263.171161085722156.958265662  730645.9836611
722200.708265662729978.275327757721940.240962476  728999.4992861
722057.579253316728584.034341693721545.905024946728298.146385357
 719619.51613608726807.868607581 718944.51613605725769.674163118

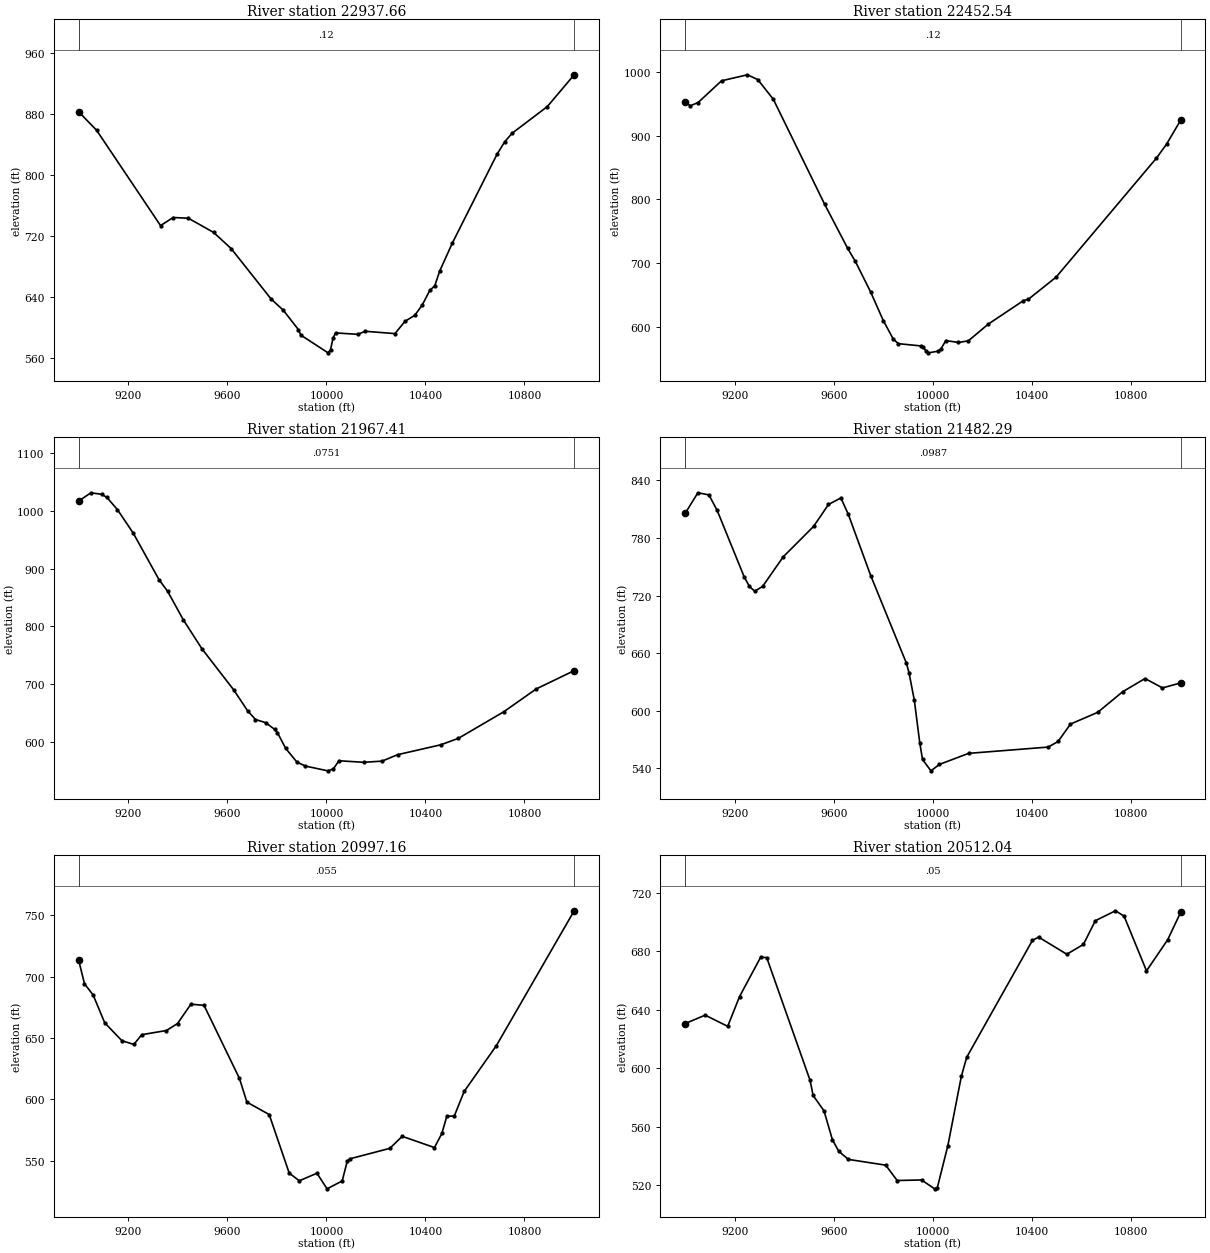
Type RM Length L Ch R = 1 ,22937.66,485.124900,485.124900,485.124900
XS GIS Cut Line= 6
727475.296834721741915.660342843727382.901033602742260.534348557
727326.877138593742568.355441017727308.909876573742770.185729411
727305.074931216743226.695551751727212.834081278743892.216490392
#Sta/Elev= 30
8999.072882.76369071.325858.71599329.915733.79489381.159744.35229442.401743.4038
9544.244724.84079615.119703.70129776.449637.74359826.551622.73689886.644597.6786
9896.644590.413510006.75567.178910016.77571.509710026.79586.241310036.81593.2964
10126.86591.384110156.87595.399310277.06592.346710317.15608.334710357.32616.3685
10387.47629.937310417.63648.881510437.73654.942110457.83674.311710508.17710.4748
10689.78827.429210720.12 843.40510750.45854.7097 10892.2889.489511000.96931.2006
#Mann= 3 , 0 , 0
8999.072    0.12       08999.072    0.12       011000.96    0.12       0
#XS Ineff= 2 , 0
       0                10078.23       0
Bank Sta=8999.072,11000.96
Exp/Cntr=0.3,0.1

Type RM Length L Ch R = 1 ,22452.54,485.124900,485.124900,485.124900
XS GIS Cut Line= 6
727080.915397725741875.103322949726956.948209074742271.699154731
726863.387787804742639.504555581 726841.21462941 742763.37913679
726803.351754073743062.796927965726674.594735264743831.182767953
#Sta/Elev= 30
8999.045952.57169019.973946.77679051.527951.79939146.192985.94519251.128995.3847
9292.856987.7568 9355.45956.99699563.023792.14789656.067722.9683 9686.87702.6815
9748.477654.84849799.773609.90519840.528580.57579860.895573.69449951.862570.1442
9961.927568.54639971.993561.91679982.059559.3169 10022.3561.987810032.36565.3989
10052.47578.624310102.84575.532110143.26578.125510224.11604.461410365.99641.2129
10386.26643.463210497.74677.990610903.37864.759410943.96886.490511000.99924.0838
#Mann= 3 , 0 , 0
8999.045    0.12       08999.045    0.12       011000.99    0.12       0
#XS Ineff= 2 , 0
       0                10056.44       0
Bank Sta=8999.045,11000.99
Exp/Cntr=0.3,0.1

Type RM Length L Ch R = 1 ,21967.41,485.125000,485.125000,485.125000
XS GIS Cut Line= 6
726759.328362231741778.501898048726532.660855831742375.289916593
726331.747209347742778.189207066726279.239913377742906.207489771
726218.739624672743150.060822281726135.769769562743666.635761084
#Sta/Elev= 30
8999.0321016.3999048.8271030.7189091.6631028.0369113.081 1022.78 9155.88 1001.58
 9219.85960.92249323.977 880.5769358.453860.72949422.424811.06279497.296761.3448
9626.378690.00039681.544654.46969713.525639.35579754.421633.95329790.859622.3076
9801.936616.89059835.665589.35119880.963565.82729914.937559.014410005.52550.7436
10028.02554.057610050.52568.1596 10150.1565.4724   10225567.525410287.83 578.649
10462.39595.732710533.47606.893510715.85 652.52110847.45 692.05111000.95723.7203
#Mann= 3 , 0 , 0
8999.032  0.0751       08999.032  0.0751       011000.95  0.0751       0
#XS Ineff= 2 , 0
       0                               0
Bank Sta=8999.032,11000.95
Exp/Cntr=0.3,0.1

Type RM Length L Ch R = 1 ,21482.29,485.124900,485.124900,485.124900
XS GIS Cut Line= 6
726035.779088756741599.159220409725911.148704634741878.624731194
725853.574808874742174.100328702725877.196017779742397.615040963
726009.461107376 742785.93387797725965.304273337743537.797477869
#Sta/Elev= 30
8999.103805.50819050.713827.08619095.384824.88989128.545808.80419237.599739.6149
9258.916729.54849280.233724.55989312.097729.54979395.565760.41999518.063792.0245
9578.317814.88269628.411 821.7349658.412804.5983 9748.79740.90669893.075649.6694
9903.798639.51859925.245610.7966  9947.1566.51289958.192549.37349992.144537.5233
10026.66544.225410144.43555.7166 10465.8562.269310505.83568.086210555.89586.2194
10666.15598.477510766.51619.860810857.05 633.63610927.55623.883211000.87629.0828
#Mann= 3 , 0 , 0
8999.103  0.0987       08999.103  0.0987       011000.87  0.0987       0
#XS Ineff= 2 , 0
       0                               0
Bank Sta=8999.103,11000.87
Exp/Cntr=0.3,0.1

Type RM Length L Ch R = 1 ,20997.16,485.124900,485.124900,485.124900
XS GIS Cut Line= 6
725708.286582568741774.763840242725510.150712063742139.605386633
725451.677682289742352.442963943725546.411972558743116.656697351
725536.036952428743377.267769392725482.836400255743704.616521072
#Sta/Elev= 30
8999.074713.40039022.711694.08569057.754684.93739104.478662.29649174.023 647.684
9222.277644.71259253.912652.62659353.905656.02289398.638661.72769452.672677.4785
9505.659676.5069 9648.75616.98649678.778597.69349768.942587.55169849.808539.8427
9890.567 533.6129961.894 539.75310002.66 527.04310063.77533.464710084.05549.4465
 10094.2 551.46810256.03560.017610306.32569.8115 10436.5 560.671 10466.5572.1551
 10486.5586.2472 10516.5586.300810556.55606.3925   10687643.816211000.92753.5712
#Mann= 3 , 0 , 0
8999.074   0.055       08999.074   0.055       011000.92   0.055       0
#XS Ineff= 2 , 0
       0                               0
Bank Sta=8999.074,11000.92
Exp/Cntr=0.3,0.1

Type RM Length L Ch R = 1 ,20512.04,485.124900,485.124900,485.124900
XS GIS Cut Line= 6
 725579.75073068741921.620043079725379.705202183742217.422175503
725099.449771127 742577.67178551724964.990100915742892.360929723
724875.609698414743075.072113771724552.863069495  743629.8798843
#Sta/Elev= 30
8999.065  630.629080.002636.39339171.139628.74899219.144649.14239304.439676.1044
9328.834675.77919503.748591.84789516.307581.42599560.294570.82359593.993551.2239
9619.888543.14219658.731 537.6329809.604533.68759855.733523.18149954.184523.5563
10007.27  517.4810017.89518.197310060.66547.126310114.97594.454110136.69607.5572
10402.32687.593610427.09689.836710541.18678.088210608.37684.871810656.32701.0529
10737.64707.856310772.51704.182710863.04666.717310948.31687.943811000.96706.7477
#Mann= 3 , 0 , 0
8999.065    0.05       08999.065    0.05       011000.96    0.05       0
#XS Ineff= 2 , 0
       0                               0
Bank Sta=8999.065,11000.96
Exp/Cntr=0.3,0.1

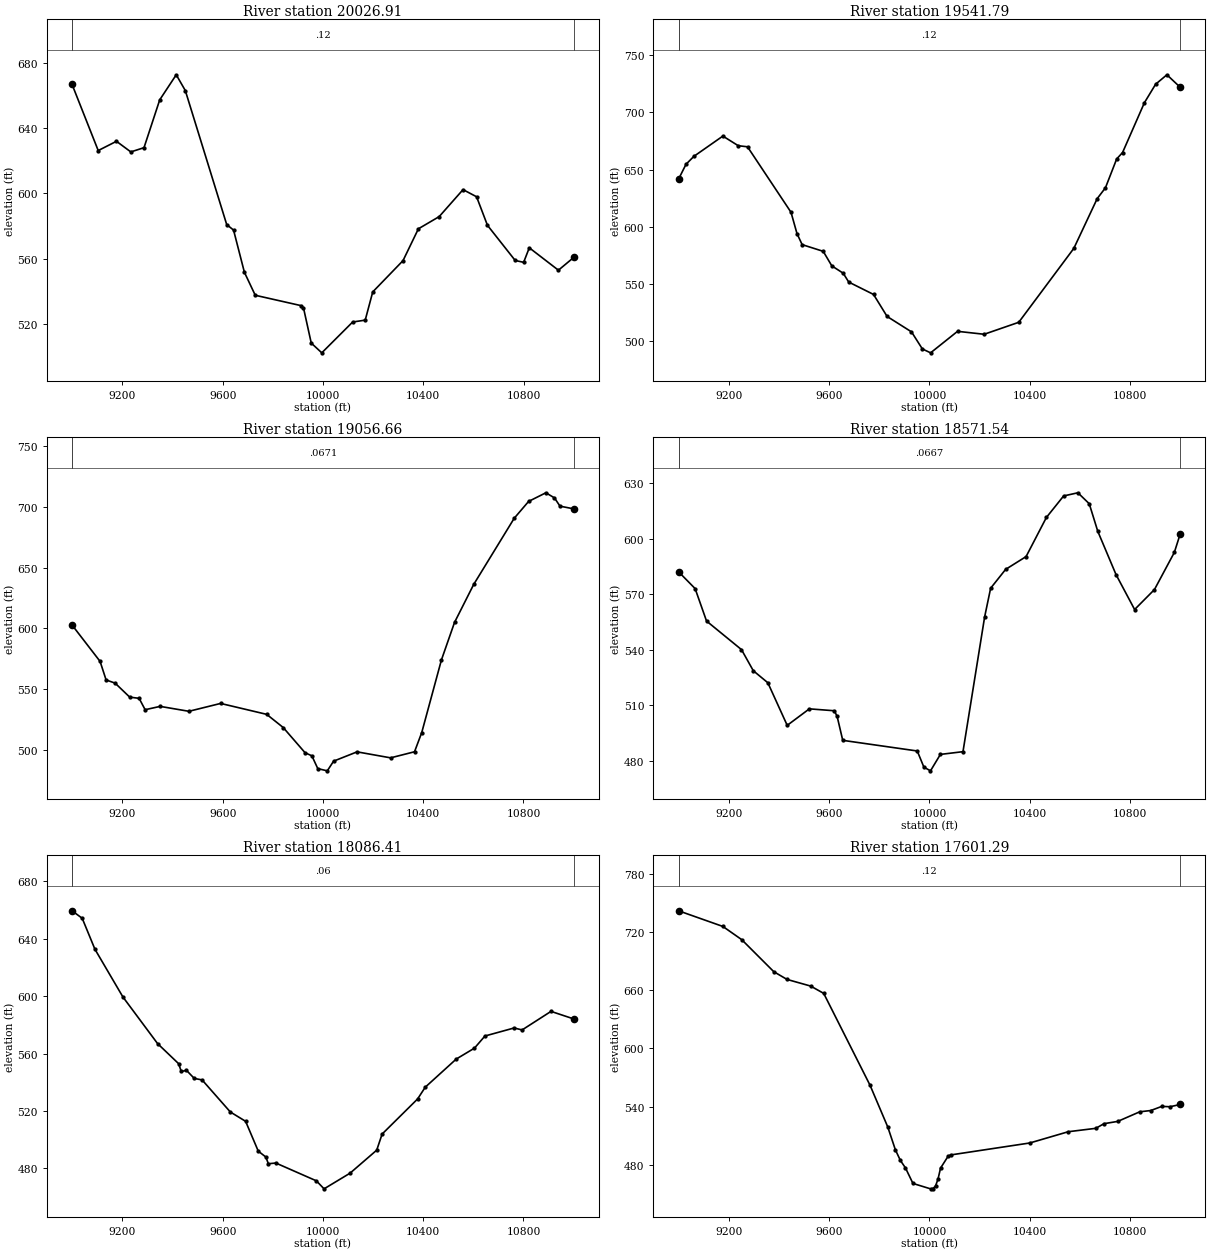
Type RM Length L Ch R = 1 ,20026.91,485.125000,485.125000,485.125000
XS GIS Cut Line= 6
725627.600410448741838.674475802725352.680668184742217.911229004
 725173.71265559742361.849417777 725031.43307777742388.524358557
724537.506107358742347.993295727 723940.30621656742606.107759601
#Sta/Elev= 30
8999.112666.84739103.419626.2904 9176.22631.97299233.461625.46399286.079628.0543
  9348.8657.39319414.664 672.769 9450.88663.08429616.012580.89649643.365577.5093
9686.582551.63349729.901537.53879912.125531.20329922.312529.81899953.285508.2163
9995.292502.230410118.48521.138910168.55522.290910198.57539.591910319.39558.7951
 10380.7578.309410463.65585.786810558.81602.334910612.85597.945410656.16580.4508
10766.82558.885810800.52557.744810823.08566.658510939.27552.913211000.88  560.81
#Mann= 3 , 0 , 0
8999.112    0.12       08999.112    0.12       011000.88    0.12       0
#XS Ineff= 2 , 0
       0                10267.04       0
Bank Sta=8999.112,11000.88
Exp/Cntr=0.3,0.1

Type RM Length L Ch R = 1 ,19541.79,485.124900,485.124900,485.124900
XS GIS Cut Line= 6
725669.594141064741354.613970419725400.360475425741588.833360836
725162.686996772741736.227322087 724791.15216509741898.140412488
724284.403120449  742087.4462592723907.634321216742269.109925639
#Sta/Elev= 30
8999.058641.60859028.792654.58759060.316661.54159175.943679.22999237.275670.8278
9274.208669.88219447.779612.74469471.597 594.1549492.207584.49359576.294578.6437
9610.606565.95459656.077559.54149678.089551.82029777.067541.0196 9831.14521.8116
9928.473508.3697 9971.84493.451410004.66490.062310112.19508.830410218.37 506.273
10356.35516.713210576.14581.245810669.27624.629310702.26634.1116   10747659.2585
10770.56664.885510857.68708.346510902.42724.485810947.42732.725911000.97721.7239
#Mann= 3 , 0 , 0
8999.058    0.12       08999.058    0.12       011000.97    0.12       0
#XS Ineff= 2 , 0
       0                10274.26       0
Bank Sta=8999.058,11000.97
Exp/Cntr=0.3,0.1

Type RM Length L Ch R = 1 ,19056.66,485.124900,485.124900,485.124900
XS GIS Cut Line= 6
725408.326139034740888.383804276724878.475192008741242.111187193
724440.278232669741576.060625965724303.089355678741673.965325526
 724101.66925952741800.928847464723747.629208631742002.111725431
#Sta/Elev= 30
8999.018 602.7699110.814572.92279134.773557.7114 9170.71555.10279228.991543.6081
9266.542542.6128  9290.5533.27599350.396536.00679465.111531.97889591.738538.4302
 9775.59529.46359841.448 518.6429928.732497.93749955.736495.43569979.334484.9285
10017.22483.104810042.44491.0544 10136.1498.689410269.89493.766710365.31498.7649
10394.09 514.52210472.62574.129410524.94604.950610601.47636.136710763.18690.4712
10820.52704.260910889.32711.339410923.73707.118810945.59700.352511000.98698.1307
#Mann= 3 , 0 , 0
8999.018  0.0671       08999.018  0.0671       011000.98  0.0671       0
#XS Ineff= 2 , 0
       0                10170.54       0
Bank Sta=8999.018,11000.98
Exp/Cntr=0.3,0.1

Type RM Length L Ch R = 1 ,18571.54,485.125000,485.125000,485.125000
XS GIS Cut Line= 6
725116.393125077740655.949281676724419.299846695740993.533730187
724327.481456235741053.434302618724145.686409774741205.783227709
724000.942031028 741306.46721652723383.845187136741644.935500427
#Sta/Elev= 30
8999.038582.13269065.219573.03429110.781555.51759250.223540.09999297.319528.7073
 9355.29522.22789432.609499.22769520.972508.13679620.627507.10819631.805 504.056
9654.161491.14519951.422485.39719977.857476.686510004.24474.684910043.71483.5527
10133.86485.0273 10220.2557.723410244.17573.232610303.91583.392410385.62590.3163
10466.62611.4196 10535.4623.036510592.32624.743810637.58618.832610671.53603.9938
10744.61580.541110818.62561.739810897.82572.533510977.03592.546611000.96602.7288
#Mann= 3 , 0 , 0
8999.038  0.0667       08999.038  0.0667       011000.96  0.0667       0
#XS Ineff= 2 , 0
       0                10055.03       0
Bank Sta=8999.038,11000.96
Exp/Cntr=0.3,0.1

Type RM Length L Ch R = 1 ,18086.41,485.124900,485.124900,485.124900
XS GIS Cut Line= 6
725142.157017646740418.862453029724870.911624225740528.992223187
724656.724206434740594.869513268723753.636216813740727.198476277
723532.936968788740787.942870182723213.139990595740909.127958958
#Sta/Elev= 30
 8999.09 659.4389039.561654.19449090.273632.64519201.908 599.3949340.258566.8954
9424.372552.87299434.758547.4607 9455.53548.24739486.688542.62359517.821541.5984
9630.529519.24059691.394512.75939741.949491.9642 9772.13 487.869 9782.19483.1963
9811.997483.6888 9973.56471.294910004.42465.705310108.16476.627810214.43492.6493
10236.01503.876410377.54528.323310408.11536.528710531.57556.114110604.42563.7359
10646.25572.189810762.58 577.78310794.49576.416110909.76589.344411000.93584.0583
#Mann= 3 , 0 , 0
 8999.09    0.06       0 8999.09    0.06       011000.93    0.06       0
#XS Ineff= 2 , 0
       0                               0
Bank Sta=8999.09,11000.93
Exp/Cntr=0.3,0.1

Type RM Length L Ch R = 1 ,17601.29,485.124900,485.124900,485.124900
XS GIS Cut Line= 6
725107.522711158739924.763790791 724784.91736444740056.167470335
724513.930605219740140.025771939724043.464976764740194.533341276
723926.741995437740222.529725622 723217.50076673740533.627518012
#Sta/Elev= 30
8999.086741.8098 9175.94725.65679251.153712.05319379.037679.02949431.735671.0603
9526.334 664.181 9578.24656.65999763.096 561.9519833.939 518.8419864.098495.4653
9884.178484.42979904.258476.82129934.306460.738510004.34455.181410014.34455.5083
10024.34458.131410034.35465.354310044.35 476.55610074.44488.751710084.48490.1174
10400.32502.4482 10553.9514.0613 10663.6517.557310696.51522.346910751.36  524.71
10839.12534.600510882.99535.903110926.87540.158710959.78539.828911000.92 542.146
#Mann= 3 , 0 , 0
8999.086    0.12       08999.086    0.12       011000.92    0.12       0
#XS Ineff= 2 , 0
       0                               0
Bank Sta=8999.086,11000.92
Exp/Cntr=0.3,0.1

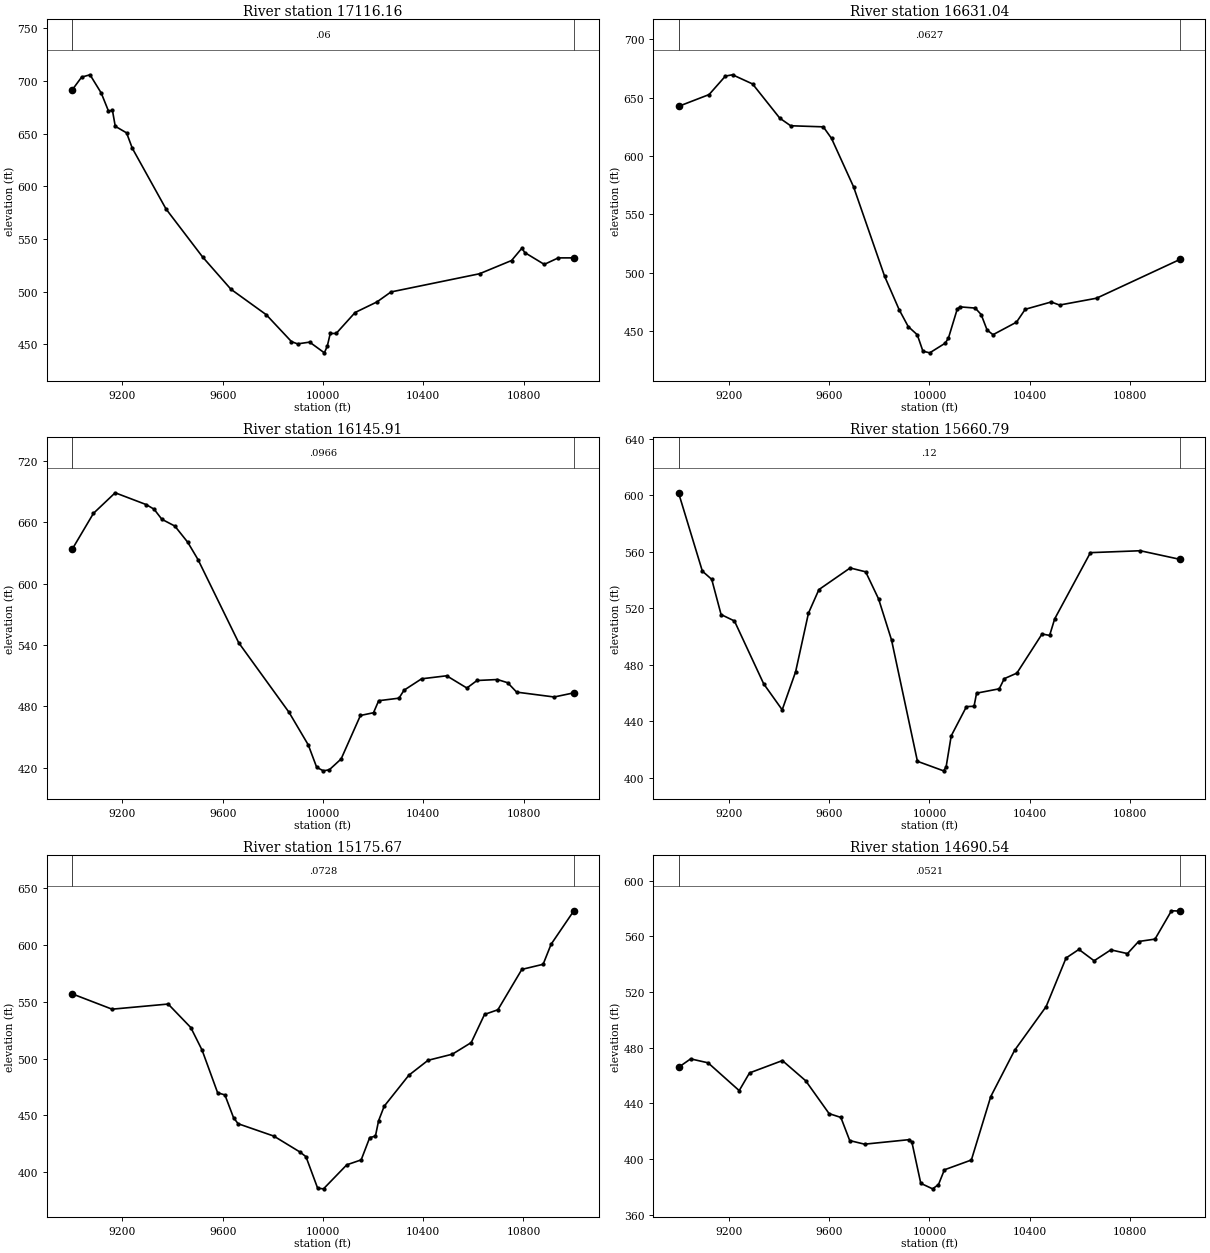
Type RM Length L Ch R = 1 ,17116.16,485.124900,485.124900,485.124900
XS GIS Cut Line= 6
724649.025378356739250.012533173724321.001786831739423.064203355
724076.670737216739595.376546092723773.723191075739991.345220856
723635.388490474740123.610100559723079.097625745740435.690319121
#Sta/Elev= 30
8999.072691.19949037.131703.47619070.688705.7126 9115.43688.40249144.116671.4327
9160.172671.90169171.358656.87089216.576650.60649239.202636.11859373.754578.4722
9519.729532.93299632.727502.31719773.708478.15569874.355452.63479898.708450.4775
9946.904452.157910005.52441.989210017.29448.389810029.06 460.374 10052.6460.3501
10128.18480.237210215.18 490.25210271.35499.737210624.66516.995610752.42529.5583
10793.74541.290610804.88537.116110882.88525.8695 10938.6532.037211000.89532.0642
#Mann= 3 , 0 , 0
8999.072    0.06       08999.072    0.06       011000.89    0.06       0
#XS Ineff= 2 , 0
       0                               0
Bank Sta=8999.072,11000.89
Exp/Cntr=0.3,0.1

Type RM Length L Ch R = 1 ,16631.04,485.125000,485.125000,485.125000
XS GIS Cut Line= 6
724507.357645191739051.562654631723816.350684292739348.314714897
723701.481961949739413.709394404723240.845228631739713.682443668
723005.326291418739838.377176087722732.821127363739966.182173186
#Sta/Elev= 30
8999.038642.5855  9120.9652.70049185.975668.55889214.541669.68899294.434661.8126
9402.893632.47949446.277625.94739576.548625.00859609.322615.12819697.165573.6298
9820.988496.89869879.285468.07929915.322453.64239951.499446.59099974.044 432.489
10001.25431.078810063.14  439.3910076.04443.895610111.33468.894410123.37 470.506
10182.77469.486710206.42463.929210230.07450.641510253.71446.650110347.31457.3889
10382.16468.456410485.78474.7232 10519.1472.084510666.61477.946311000.96511.3804
#Mann= 3 , 0 , 0
8999.038  0.0627       08999.038  0.0627       011000.96  0.0627       0
#XS Ineff= 2 , 0
       0                 10145.7       0
Bank Sta=8999.038,11000.96
Exp/Cntr=0.3,0.1

Type RM Length L Ch R = 1 ,16145.91,485.124900,485.124900,485.124900
XS GIS Cut Line= 6
724365.145280803738997.826341694723638.058807236739179.867120071
723506.991389706739168.807811661723290.289078578739046.169175399
723090.736090602 739005.78598909722439.269964436739113.432303561
#Sta/Elev= 30
8999.127633.27719084.397668.57569171.086688.67149294.894677.13079326.222672.6408
9357.374662.77589409.074656.16319460.535640.34329501.535623.39039663.922542.1258
9864.856 474.0819941.448442.30259974.899420.469110001.55 416.98910025.39418.0255
10072.47428.607810149.42471.062710201.65473.768110222.25485.502910303.26487.9982
10323.34495.7551 10393.4 506.90310493.54509.863210574.09497.897510614.52505.2583
10695.95506.207210736.78503.074210772.61 493.89910922.33489.145411000.87493.1969
#Mann= 3 , 0 , 0
8999.127  0.0966       08999.127  0.0966       011000.87  0.0966       0
#XS Ineff= 2 , 0
       0                               0
Bank Sta=8999.127,11000.87
Exp/Cntr=0.3,0.1

Type RM Length L Ch R = 1 ,15660.79,485.124900,485.124900,485.124900
XS GIS Cut Line= 6
724503.547069408738377.266580728724034.148747132738544.519193063
 723501.09023848738689.657941497723382.696612862738710.391180441
722950.443887081738758.120150401722564.426743323738844.349839437
#Sta/Elev= 30
8999.035601.74859094.069546.29029131.462540.44979168.796515.54389222.092511.0005
9338.743 466.5029412.606 448.1049466.124475.04179517.396516.54149559.027533.2045
9683.688548.52889745.604545.79689797.201526.57299848.799497.52319952.122411.6654
10056.23404.909910066.44  407.5810086.85429.6569 10147.7450.377410177.99450.6131
10188.03459.891310278.46462.985610298.56470.1573 10348.8474.078710449.28501.7838
10479.46500.769910499.65512.497310642.21 559.36810841.12560.716411000.91554.5761
#Mann= 3 , 0 , 0
8999.035    0.12       08999.035    0.12       011000.91    0.12       0
#XS Ineff= 2 , 0
       0                               0
Bank Sta=8999.035,11000.91
Exp/Cntr=0.3,0.1

Type RM Length L Ch R = 1 ,15175.67,485.125000,485.125000,485.125000
XS GIS Cut Line= 6
724228.239847211737762.470637846723723.521924768738017.579852394
723246.457317198738295.211751116723083.045826511 738380.31096511
722823.795298451738489.025930404722429.367293066738630.049839464
#Sta/Elev= 30
 8999.03556.98569158.563543.44749382.391 547.9739472.697527.2663  9517.8507.3568
 9579.75469.83379608.791467.92829643.203447.90669661.403442.57549803.885431.6843
9908.875417.56159932.197413.51519978.841385.763310002.17385.225110095.08406.3828
10152.43410.724110186.58430.370810209.29431.628910221.85445.145410244.24457.9797
10342.53485.261710419.14 498.41710516.27503.816610591.44514.021310644.65538.8362
10697.86542.936310793.52578.489210878.35582.980210910.16  600.6311000.96630.1086
#Mann= 3 , 0 , 0
 8999.03  0.0728       0 8999.03  0.0728       011000.96  0.0728       0
#XS Ineff= 2 , 0
       0 9879.35                       0
Bank Sta=8999.03,11000.96
Exp/Cntr=0.3,0.1

Type RM Length L Ch R = 1 ,14690.54,485.124900,485.124900,485.124900
XS GIS Cut Line= 6
723949.517407615737322.686167553723537.948451193737546.745698847
 722986.50655042737888.788905665722743.374949577738032.783030578
722479.612681533738170.149175579722202.669256202738296.313268617
#Sta/Elev= 30
8999.016 465.8829047.301471.96259116.874469.12369241.056449.16459282.274461.8782
9413.331470.73339506.219 456.2599599.741432.63359646.608429.89619682.037413.2603
9741.086410.67459920.012 413.9429930.042412.12519965.471382.545710012.65378.5848
10036.15381.635610059.65  392.2510167.31399.301510244.65444.8635 10339.6478.0476
10465.65509.547510545.03544.4334 10596.3550.604410657.01542.444310723.83550.2917
10790.11547.601710834.31556.292710899.96558.015610965.61578.369111000.98578.1638
#Mann= 3 , 0 , 0
8999.016  0.0521       08999.016  0.0521       011000.98  0.0521       0
#XS Ineff= 2 , 0
       0                               0
Bank Sta=8999.016,11000.98
Exp/Cntr=0.3,0.1

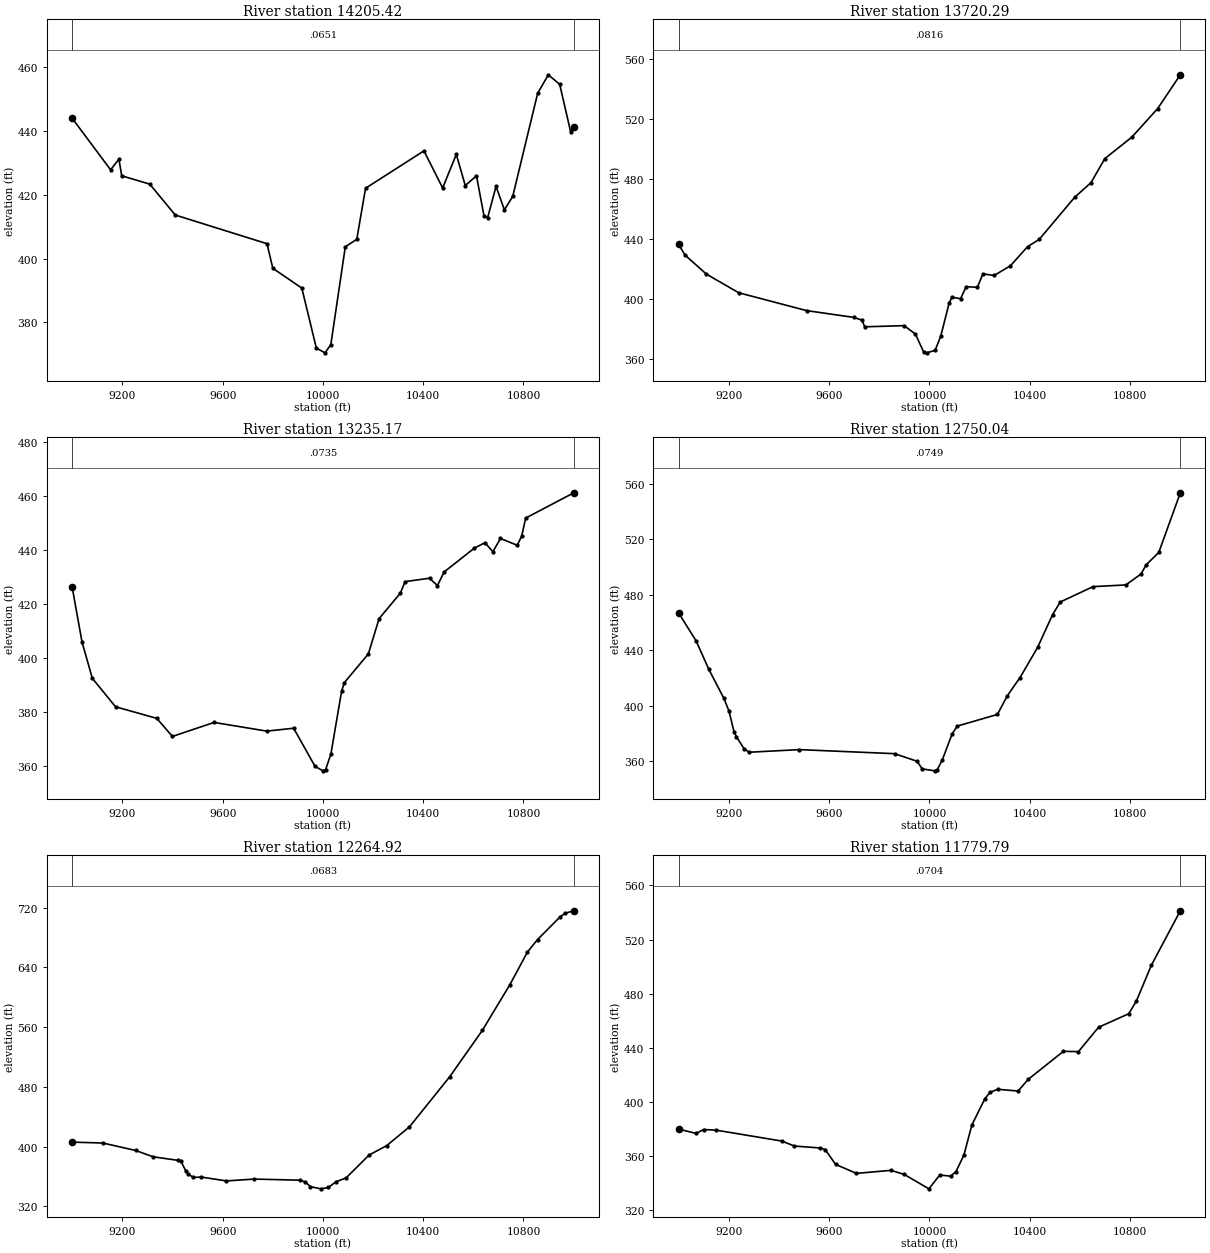
Type RM Length L Ch R = 1 ,14205.42,485.124900,485.124900,485.124900
XS GIS Cut Line= 6
723693.630912008736954.188699755723493.302586851737050.114008876
723232.135417724737186.987549981722436.956164468737638.199625625
722209.001599148737754.279418732721923.652910981 737887.29026497
#Sta/Elev= 30
8999.018444.10439152.723427.88879185.985431.20989197.072425.99479309.058423.3873
9410.668413.68899776.771404.68149799.918396.96949915.654390.75259973.521371.9186
10008.23370.426910031.34373.0006 10089.1403.713710134.87406.052910169.97422.0903
10402.91433.827310477.59422.175910531.98432.730710567.71422.949310612.41425.9878
 10642.9413.2536 10657.1412.886910690.58422.675810723.84415.3061 10757.1419.5341
 10856.6451.904210899.14457.710110944.54454.701510988.51439.675211000.98441.1906
#Mann= 3 , 0 , 0
8999.018  0.0651       08999.018  0.0651       011000.98  0.0651       0
#XS Ineff= 2 , 0
       09832.709                       0
Bank Sta=8999.018,11000.98
Exp/Cntr=0.3,0.1

Type RM Length L Ch R = 1 ,13720.29,485.125000,485.125000,485.125000
XS GIS Cut Line= 6
723519.547348343736584.809188542723245.677624532736688.426114323
722999.381448584736794.201560056722228.968177089737177.721826598
721958.938666143737300.081809788721697.165168431737409.974090956
#Sta/Elev= 30
8999.022436.46439025.162429.21049110.356416.56459238.907404.18629510.049392.2902
9697.439387.79239730.831385.97579741.961381.50149898.927382.27029943.939376.6862
9977.698364.50479988.951364.167910022.76365.821510045.29375.344410079.09397.6266
10090.36401.194710124.15400.211610146.69408.211410191.29407.842210213.55416.7835
10258.07415.681810323.29422.167410391.63434.903910437.91439.688710579.08467.6889
10644.76477.521210699.49 493.44410808.11507.888510910.62526.840811000.98549.3329
#Mann= 3 , 0 , 0
8999.022  0.0816       08999.022  0.0816       011000.98  0.0816       0
#XS Ineff= 2 , 0
       09761.765        10587.49       0
Bank Sta=8999.022,11000.98
Exp/Cntr=0.3,0.1

Type RM Length L Ch R = 1 ,13235.17,485.124900,485.124900,485.124900
XS GIS Cut Line= 6
723333.695548288736278.935217035722986.535405594736362.649427466
722717.501817344736440.078126101 722587.25798807736484.329636021
722017.686650968736692.625968372721426.677884852736882.505187498
#Sta/Elev= 30
8999.027426.47199038.776405.90699079.864392.48779172.312381.93169337.109377.6263
9399.224370.92829565.557376.11849776.099372.89749882.979373.97469968.483359.8238
 10000.1358.176810010.64358.627510031.72364.448810074.39387.685910085.07390.8416
10181.18 401.53410223.86414.596710308.76424.040810327.57428.312910425.17429.5784
10456.77426.847610483.17431.873610604.25440.758510646.39442.7321 10677.9439.3962
10708.17 444.313 10775.1 441.78210793.17445.265610808.56451.865811000.98461.2474
#Mann= 3 , 0 , 0
8999.027  0.0735       08999.027  0.0735       011000.98  0.0735       0
#XS Ineff= 2 , 0
       09608.047        10048.26       0
Bank Sta=8999.027,11000.98
Exp/Cntr=0.3,0.1

Type RM Length L Ch R = 1 ,12750.04,485.124900,485.124900,485.124900
XS GIS Cut Line= 6
723285.148254613736035.857720909722769.942657094736077.791423303
722199.273318271736090.198981988721913.388238394736103.295815743
721639.431474137736128.664489023721290.212559638736178.545240483
#Sta/Elev= 30
8999.019467.02799069.551446.64959119.824426.22369180.089405.25189200.163396.1804
9220.238381.32919230.275377.52059260.387369.02779280.462366.42219480.879 368.317
9861.074365.39049951.082359.87729971.084354.416110021.09353.002110031.09353.8144
 10051.1360.738210091.11379.842210111.13385.297410271.26393.696710311.33407.3251
10361.41420.285310431.61442.0549 10491.5465.740710521.96474.809510652.66485.9022
10783.78487.1522 10844.3495.038210864.51501.590710915.13510.626311000.98553.6319
#Mann= 3 , 0 , 0
8999.019  0.0749       08999.019  0.0749       011000.98  0.0749       0
#XS Ineff= 2 , 0
       0  9583.5        10136.55       0
Bank Sta=8999.019,11000.98
Exp/Cntr=0.3,0.1

Type RM Length L Ch R = 1 ,12264.92,485.124900,485.124900,485.124900
XS GIS Cut Line= 6
723338.345016298735722.998012527722870.629108736735698.882888829
722179.062976878735580.035509616721918.017820473 735548.17341942
721659.907174523 735538.67126219721350.351468776735554.707945547
#Sta/Elev= 30
 8999.03406.10879122.376404.8653  9252.5394.93779322.661386.45359423.097381.6425
9433.151380.54879453.259367.32649463.313363.07479483.474358.83579513.738359.3915
9614.811354.22299726.441356.66049909.526355.15399929.869352.66159950.211346.5984
9990.897343.599310021.43345.404210051.91353.052410092.49358.295810183.73388.7476
10254.43 401.42910345.11426.580910505.69493.578910635.81555.588210745.83616.8317
10815.86 660.42510855.93677.050710946.16707.527110966.21  712.3211000.95715.6191
#Mann= 3 , 0 , 0
 8999.03  0.0683       0 8999.03  0.0683       011000.95  0.0683       0
#XS Ineff= 2 , 0
       09686.317                       0
Bank Sta=8999.03,11000.95
Exp/Cntr=0.3,0.1

Type RM Length L Ch R = 1 ,11779.79,485.125000,485.125000,485.125000
XS GIS Cut Line= 6
723435.188963967735341.526786311722890.633234729735283.849772389
 722304.06028973735077.959300995722115.155192922735036.760465126
721835.631187006735028.884446649721480.569443026735066.023688659
#Sta/Elev= 30
8999.072380.04139069.292376.84799099.306379.70799149.343379.24339410.874371.1997
9461.597367.51149563.728366.09459584.301364.92239625.476353.98219708.801347.3054
 9846.36349.56499899.922346.51679997.784335.8981 10041.2346.129410084.34345.2724
10105.57348.554910137.42360.739110169.26 383.06310221.28402.524410241.89407.2021
 10272.7409.446510353.84408.153210394.12416.779710534.39437.4816 10594.4437.2602
10674.51455.234810794.89465.241210825.06474.4144 10885.5501.119511000.91541.3192
#Mann= 3 , 0 , 0
8999.072  0.0704       08999.072  0.0704       011000.91  0.0704       0
#XS Ineff= 2 , 0
       09763.946                       0
Bank Sta=8999.072,11000.91
Exp/Cntr=0.3,0.1

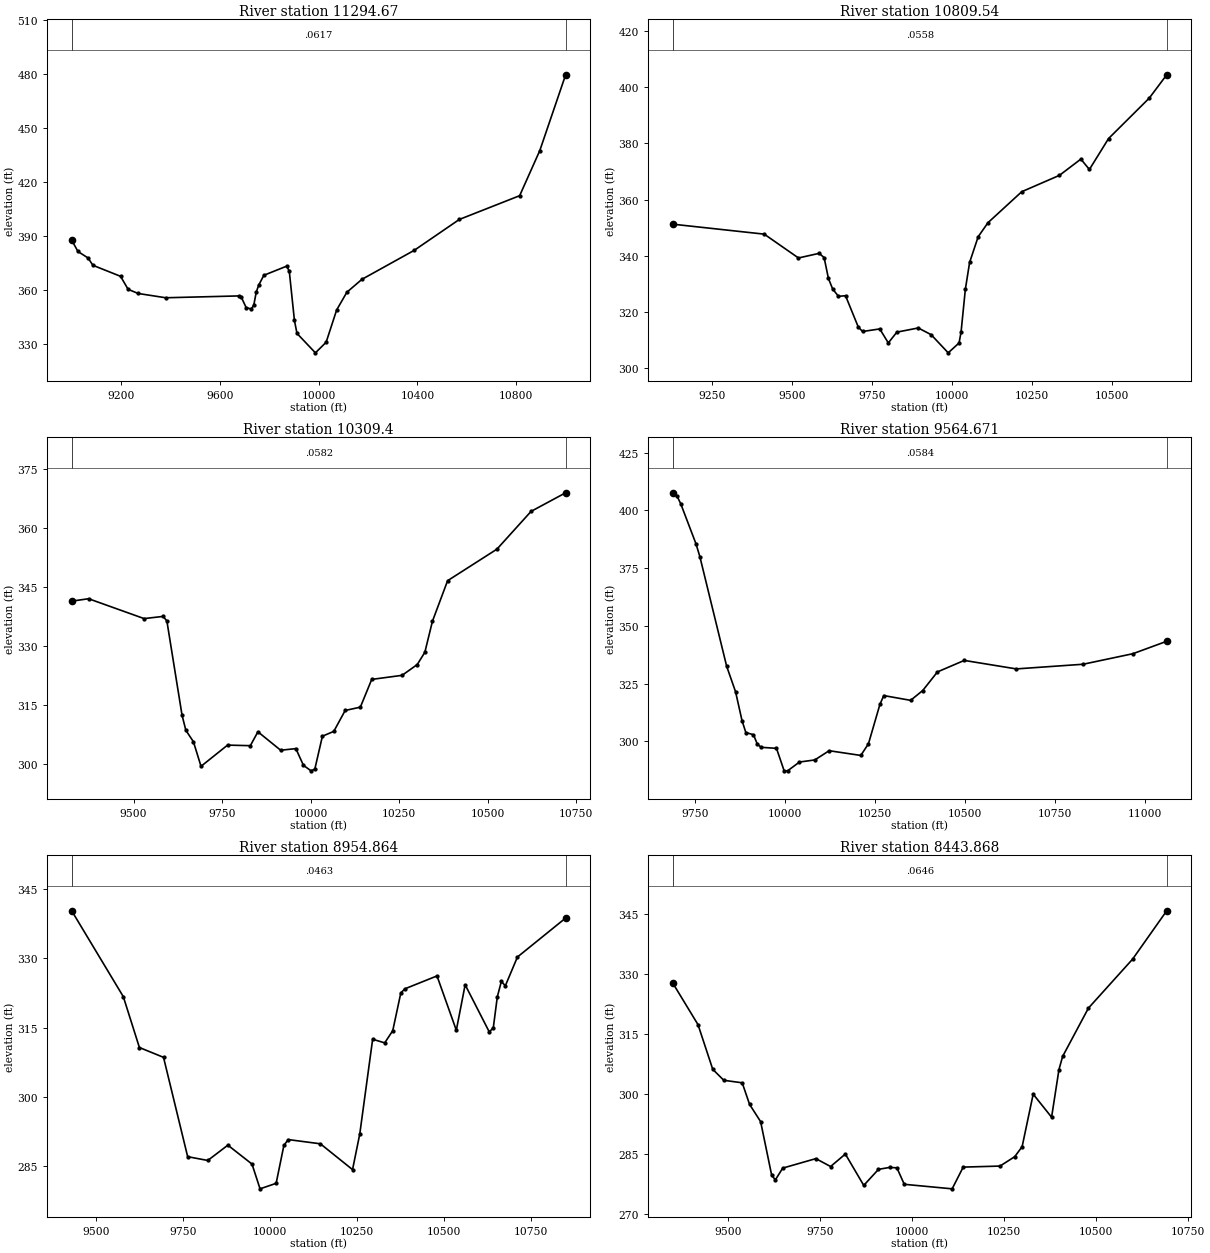
Type RM Length L Ch R = 1 ,11294.67,485.124900,485.124900,485.124900
XS GIS Cut Line= 6
723579.913030779734485.214607107722811.081638263734632.229263568
722680.231428369734666.357712131722481.459470998734735.918462319
722085.739915499734797.742586242 721622.24093066734888.184754427
#Sta/Elev= 30
8999.031387.56879024.356381.19839065.019377.6121 9085.35373.49589197.171367.3791
9227.668360.16069268.331357.83659380.152355.4513 9675.52356.47329685.752355.9615
9706.216349.9851 9726.68349.20919736.912351.22799747.144358.68879757.376 362.576
 9777.84367.95169870.564373.04439880.959370.16919901.748342.86849912.143335.6102
9986.793324.812710030.24330.695510072.92348.663910114.25358.515410175.28365.6987
10387.51381.853610570.16399.019510814.56  412.2310896.15437.303411000.95479.4931
#Mann= 3 , 0 , 0
8999.031  0.0617       08999.031  0.0617       011000.95  0.0617       0
#XS Ineff= 2 , 0
       09862.451                       0
Bank Sta=8999.031,11000.95
Exp/Cntr=0.3,0.1

Type RM Length L Ch R = 1 ,10809.54,500.137800,500.137800,500.137800
XS GIS Cut Line= 2
722978.808795363733731.313820541721824.294906497734755.619376123
#Sta/Elev= 30
9126.754351.22689412.583347.68389519.531 339.2069584.343340.85649599.742 339.326
 9613.11331.93329626.478328.14139644.614325.55249666.584325.77759706.689314.5614
9720.058313.04289773.531313.96039800.268308.98049827.005312.81959893.848314.2988
9933.953311.92159987.427305.449910021.31308.959310027.53312.7972 10040.9328.0011
10054.27337.618410081.01 346.75710111.72351.760810217.19362.783310335.01368.6058
10401.85374.382710428.59370.697210488.41 381.69510615.74396.104810670.16 404.388
#Mann= 3 , 0 , 0
9126.754  0.0558       09126.754  0.0558       010670.16  0.0558       0
#XS Ineff= 2 , 0
       0                               0
Bank Sta=9126.754,10670.16
Exp/Cntr=0.3,0.1

Type RM Length L Ch R = 1 , 10309.4,744.731500,744.731500,744.731500
XS GIS Cut Line= 2
722635.926850915 733687.91104278721333.843517601734187.042987213
#Sta/Elev= 30
 9325.38341.43619373.123342.04619529.854337.00629583.402337.56229594.112336.4246
 9636.95312.48759647.659308.67259669.078 305.7629690.497299.52849765.464304.9101
9829.722 304.7639851.141308.28549915.398303.60339958.236304.02349979.655299.7805
10001.07298.381210011.78298.8191 10033.2307.172610065.33308.389710097.46313.6989
 10140.3314.537710172.43321.5798 10258.1322.611510300.94325.348110322.36328.4569
10343.78336.325110386.62346.621510525.84354.621910622.23364.206110719.85368.9272
#Mann= 3 , 0 , 0
 9325.38  0.0582       0 9325.38  0.0582       010719.85  0.0582       0
#XS Ineff= 2 , 0
       0                               0
Bank Sta=9325.38,10719.85
Exp/Cntr=0.3,0.1

Type RM Length L Ch R = 1 ,9564.671,609.807000,609.807000,609.807000
XS GIS Cut Line= 2
722315.695744902733104.575644121721026.670432001733579.632163927
#Sta/Elev= 30
9686.878407.62469698.277406.34449708.934402.91969751.564385.48979762.222 379.999
9836.824332.49789861.614321.44959879.454309.02779890.112303.83669911.427302.8773
9922.084298.79929932.742297.43529975.372296.98239996.687287.250310006.21287.2478
10039.32291.060210081.95291.962310121.88295.960810209.84293.913610231.15 298.967
10263.12316.074210273.78319.834610348.38317.762810382.14322.023310422.99 330.073
10497.59335.050610642.41331.375410827.97333.389410966.52337.952911060.66343.3367
#Mann= 3 , 0 , 0
9686.878  0.0584       09686.878  0.0584       011060.66  0.0584       0
#XS Ineff= 2 , 0
       0                               0
Bank Sta=9686.878,11060.66
Exp/Cntr=0.3,0.1

Type RM Length L Ch R = 1 ,8954.864,510.996500,510.996500,510.996500
XS GIS Cut Line= 2
722093.392128706732507.355487213720865.093517631733223.501320541
#Sta/Elev= 30
9429.016340.23859577.637321.68719623.939310.69869693.392308.57439762.845287.1157
9820.723286.29639878.601 289.6029948.054 285.5159971.205 280.16710017.51281.3568
10039.81 289.54110052.23290.809910144.84 289.89810237.44284.3204 10258.2291.9915
10295.32312.487510330.05311.7014 10353.2314.340110376.35322.469310387.93323.3736
10480.53326.163610536.15314.428510561.56324.255610631.01314.064510642.59314.9585
10654.16321.648210665.74324.961110677.31324.043310712.04330.246410850.84338.6704
#Mann= 3 , 0 , 0
9429.016  0.0463       09429.016  0.0463       010850.84  0.0463       0
#XS Ineff= 2 , 0
       0                               0
Bank Sta=9429.016,10850.84
Exp/Cntr=0.3,0.1

Type RM Length L Ch R = 1 ,8443.868,671.434000,671.434000,671.434000
XS GIS Cut Line= 2
 721993.56573984732351.105487242720652.419906497732403.188820541
#Sta/Elev= 30
9349.445327.69849418.063317.31069458.093306.15179488.115303.40639538.153302.7785
9558.168297.38919588.191293.08049618.213279.69619628.221278.52519648.236281.4686
9738.304283.83839778.334281.86539818.364284.98329868.402277.15089908.432281.1588
9938.455281.6383 9958.47281.53949978.485277.422710108.58276.289710138.61281.7193
10238.68281.977210278.71284.331610298.73286.824510328.75299.943610378.79294.1835
 10398.8306.090710408.81309.375610478.86 321.43810598.95333.6824 10691.6345.7546
#Mann= 3 , 0 , 0
9349.445  0.0646       09349.445  0.0646       0 10691.6  0.0646       0
#XS Ineff= 2 , 0
       0                               0
Bank Sta=9349.445,10691.6
Exp/Cntr=0.3,0.1