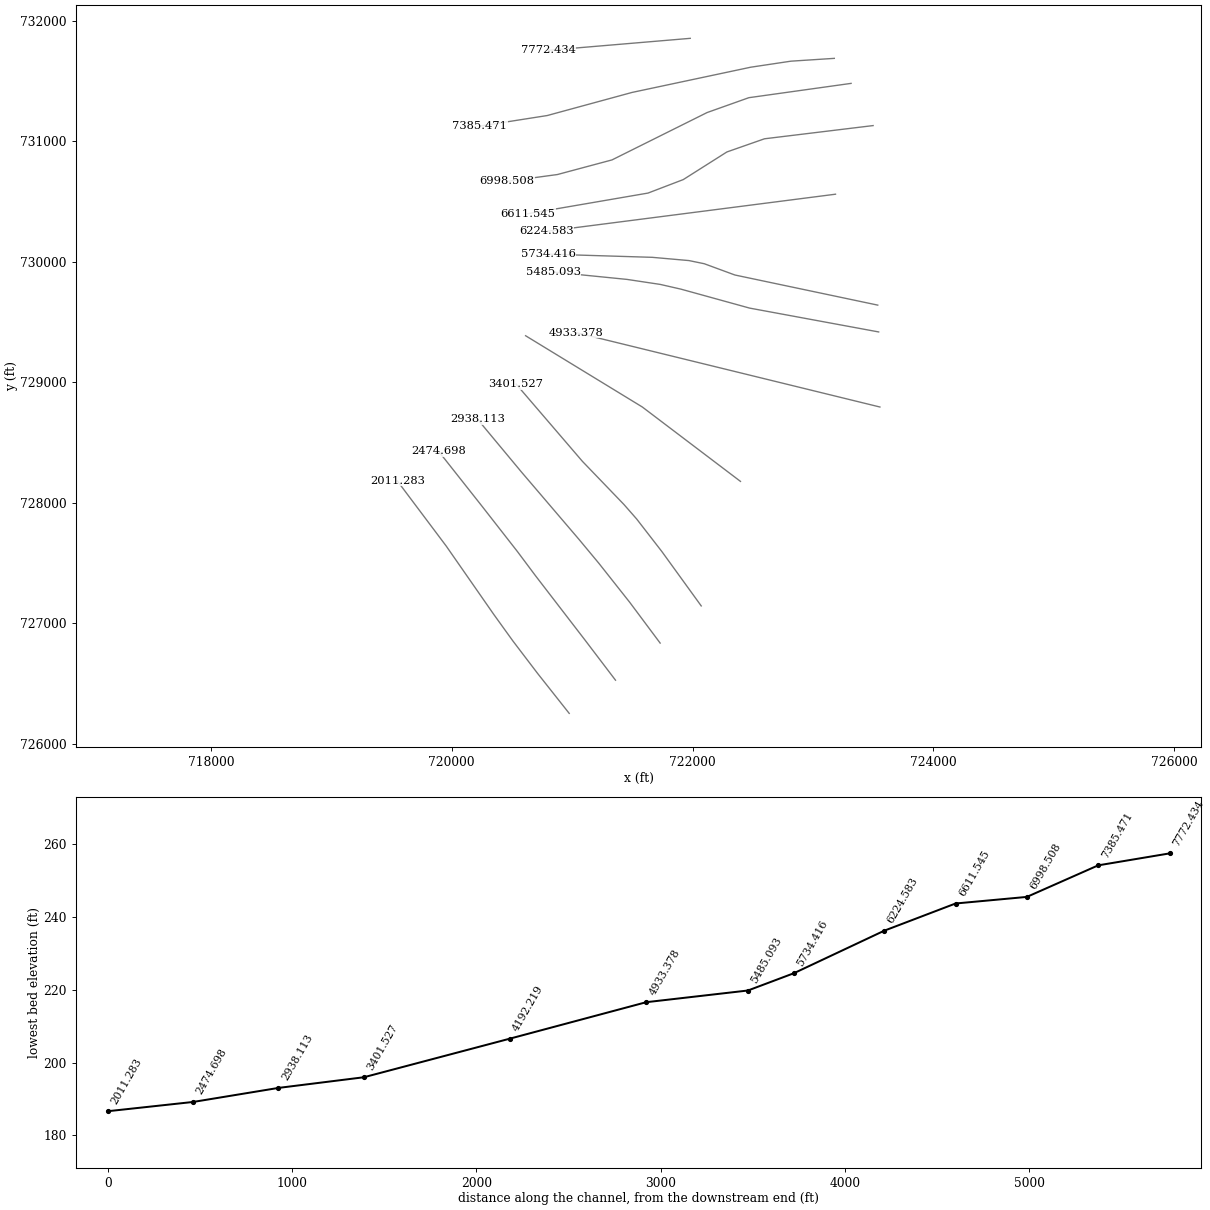
HEC-RAS study 4878_ras.prj: 4878

--- 4878_ras.g01 (geometry) --- (continued)

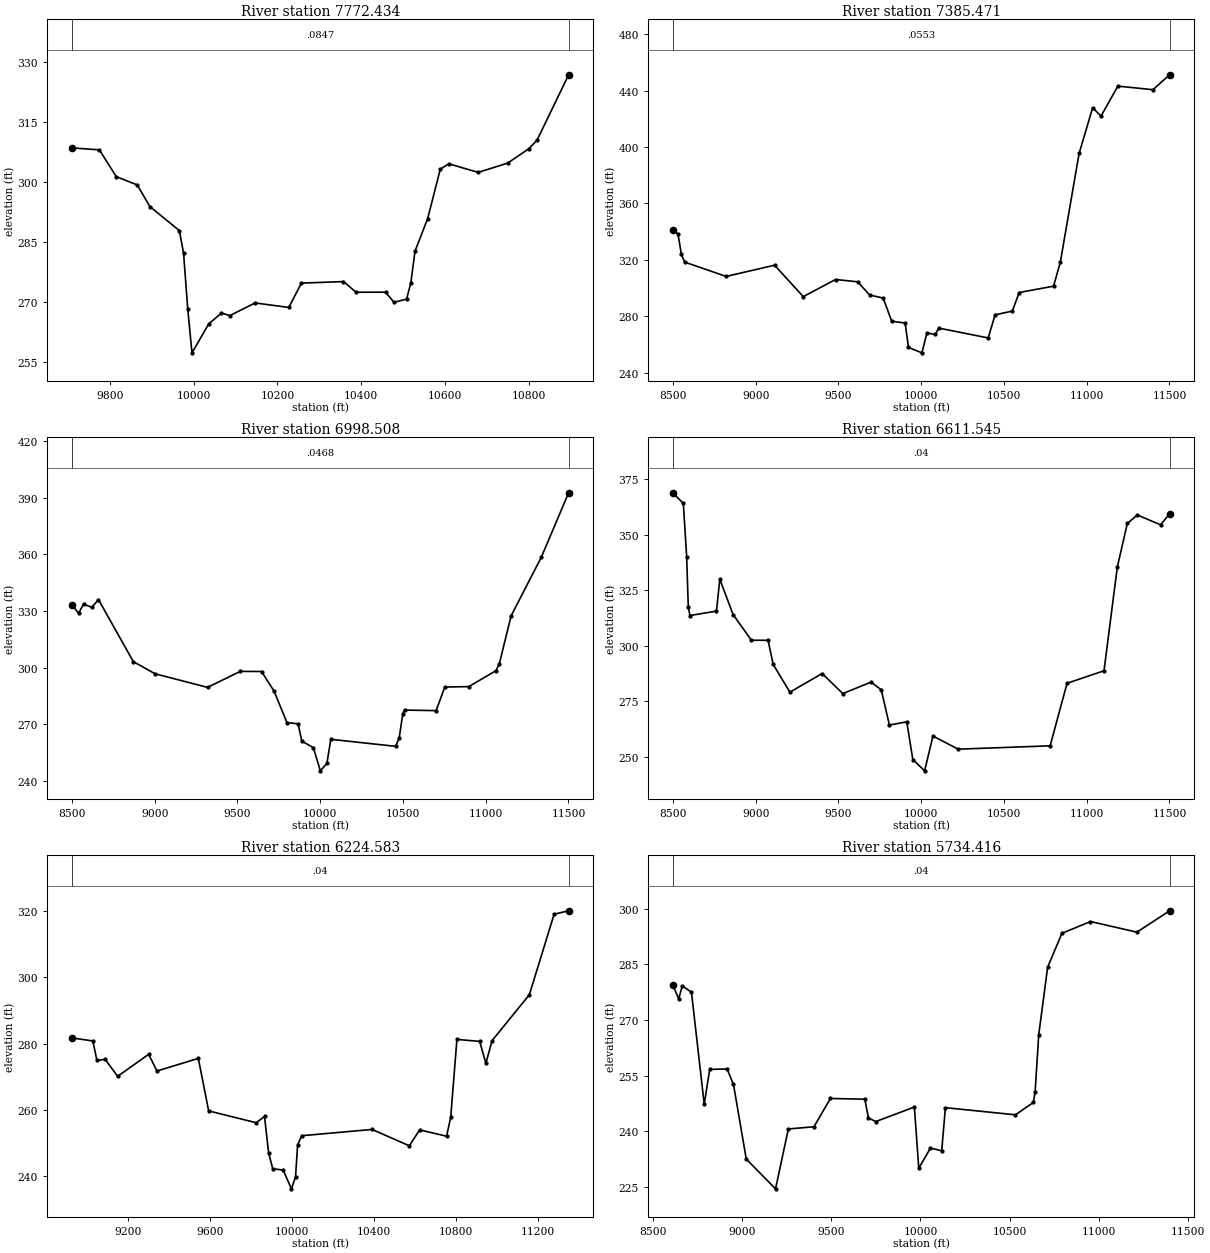
Type RM Length L Ch R = 1 ,7772.434,386.962800,386.962800,386.962800
XS GIS Cut Line= 2
721980.544906497731856.313820541720799.989350945 731756.48743166
#Sta/Elev= 30
9709.605308.50719775.383308.01169815.526301.34529865.705299.25039895.812293.8657
9966.061287.87049976.097282.21389986.133268.24149996.169257.379710036.31264.6265
10066.42267.306710086.49  266.67 10146.7269.824610226.99268.7031 10257.1274.7678
10357.45275.156910387.56272.501110457.81272.507610477.88269.981610507.99270.7885
10518.02274.821310528.06282.745910558.17290.852410588.27303.162710608.35304.5415
 10678.6302.392510748.85304.698910799.02308.254810819.09310.428410894.37326.7409
#Mann= 3 , 0 , 0
9709.605  0.0847       09709.605  0.0847       010894.37  0.0847       0
#XS Ineff= 2 , 0
       0                               0
Bank Sta=9709.605,10894.37
Exp/Cntr=0.3,0.1

Type RM Length L Ch R = 1 ,7385.471,386.962800,386.962800,386.962800
XS GIS Cut Line= 6
723176.587092082731690.072159223722816.394586128731666.696711612
722482.766247865731616.665195044721498.318037129731407.423770634
720793.154611652731215.355718695720234.846662289731127.762543951
#Sta/Elev= 30
8499.046341.3496 8530.66338.32928550.676323.99748570.693318.41968821.306308.2717
9114.062316.22189287.321293.94829482.389  306.099616.327304.45539688.384295.1406
9770.487292.8912 9821.58276.51469902.889275.24919923.112 257.93410004.14 254.104
10034.58268.179110085.31267.122210105.67271.652410404.73264.662310446.41281.0456
10550.52283.713410592.16 296.87310799.66301.3637   10841318.595110953.98395.4142
11035.77427.790511086.67421.932611188.22443.176711400.26440.636711500.96451.2133
#Mann= 3 , 0 , 0
8499.046  0.0553       08499.046  0.0553       011500.96  0.0553       0
#XS Ineff= 2 , 0
       0                10615.52       0
Bank Sta=8499.046,11500.96
Exp/Cntr=0.3,0.1

Type RM Length L Ch R = 1 ,6998.508,386.962800,386.962800,386.962800
XS GIS Cut Line= 6
723315.786453377731482.312790327722467.173404774731363.580582472
722120.398607532731240.197018639 721330.90980096730846.985518573
 720877.40176692730725.547567828720460.359287043730668.807471714
#Sta/Elev= 30
8499.059333.28558539.891328.90428569.924333.6808 8619.98331.97498660.024336.0723
 8870.93 303.2249002.158296.80989318.967289.61799517.391298.09189645.368  298.01
9721.382287.60049798.774270.98749866.247270.3266 9888.94261.16319958.131257.7405
   10001245.445610040.64249.428810063.84262.137410455.54258.409810477.18262.8092
10498.83275.751510509.58277.610310700.36277.307210752.81289.791210897.96 290.024
11061.89298.454911082.31302.090811153.42327.485911335.43358.387611500.97392.6068
#Mann= 3 , 0 , 0
8499.059  0.0468       08499.059  0.0468       011500.97  0.0468       0
#XS Ineff= 2 , 0
       0                10526.76       0
Bank Sta=8499.059,11500.97
Exp/Cntr=0.3,0.1

Type RM Length L Ch R = 1 ,6611.545,386.962800,386.962800,386.962800
XS GIS Cut Line= 6
723498.659299416731131.968113279 722596.89312519731022.335905858
722284.556488571730912.905438015721922.793613265730683.753906362
  721630.1255986730571.703010386720630.419266198730399.880980858
#Sta/Elev= 30
8499.082368.79978562.761363.99788582.767340.09048592.771317.21438602.774 313.559
8762.962315.53578783.026329.89828863.281313.99718973.887302.43899074.819302.3921
9105.245 291.6049206.661279.04219401.392287.45089526.367278.40029697.059283.5894
9758.685280.09679807.699264.25829912.884265.69599949.378248.722510020.71243.6363
10071.01259.312710223.13253.391210778.99 254.901 10881.3283.047811104.42288.6856
11185.09335.441911245.52355.010911305.79358.804411446.23354.384811500.93359.3388
#Mann= 3 , 0 , 0
8499.082    0.04       08499.082    0.04       011500.93    0.04       0
#XS Ineff= 2 , 0
       0                10484.39       0
Bank Sta=8499.082,11500.93
Exp/Cntr=0.3,0.1

Type RM Length L Ch R = 1 ,6224.583,490.166700,490.166700,490.166700
XS GIS Cut Line= 2
723186.443708897730562.213015661720784.977541536730253.453079849
#Sta/Elev= 30
 8927.45281.71969029.729280.79369049.894274.92039090.223275.24439150.717270.1174
9301.951276.76649342.281271.72969543.927275.52929594.339259.68499826.232 256.124
9866.561258.00329886.726246.9454 9906.89 242.2279957.302241.83799997.631236.1715
 10017.8239.778610027.88249.400110048.04252.198810390.84254.092710572.32249.1603
10622.73253.9651 10753.8252.049710773.97257.730410804.22281.260210915.12280.6646
10945.37274.054510975.62280.9027 11157.1294.718911278.09319.050511348.68320.0768
#Mann= 3 , 0 , 0
 8927.45    0.04       0 8927.45    0.04       011348.68    0.04       0
#XS Ineff= 2 , 0
       0 9595.25        10356.91       0
Bank Sta=8927.45,11348.68
Exp/Cntr=0.3,0.1

Type RM Length L Ch R = 1 ,5734.416,249.322400,249.322400,249.322400
XS GIS Cut Line= 6
 723537.31105116729641.323067114722350.954601616729891.465215132
722096.760822624729984.995466813721969.766676754730011.184756905
721665.084918112730038.155664012720801.999774337730064.600843638
#Sta/Elev= 30
8612.449279.44698645.474275.69018665.915279.24578717.019277.44818788.564247.2937
8819.226256.68488916.326 256.8298952.377252.64229024.101232.5087 9188.04224.5074
9259.764240.64159403.211241.23659495.427248.85439688.205 248.6769708.524243.6228
9749.357242.6314 9965.78246.55139990.465230.0463 10056.1235.513510118.93234.7532
10139.53246.3796 10532.3244.455110632.38247.784210642.38250.7219 10662.4 265.976
10712.44284.224110792.46  293.36 10952.5296.537611212.57 293.67211395.75299.4353
#Mann= 3 , 0 , 0
8612.449    0.04       08612.449    0.04       011395.75    0.04       0
#XS Ineff= 2 , 0
       09657.019        10172.19       0
Bank Sta=8612.449,11395.75
Exp/Cntr=0.3,0.1

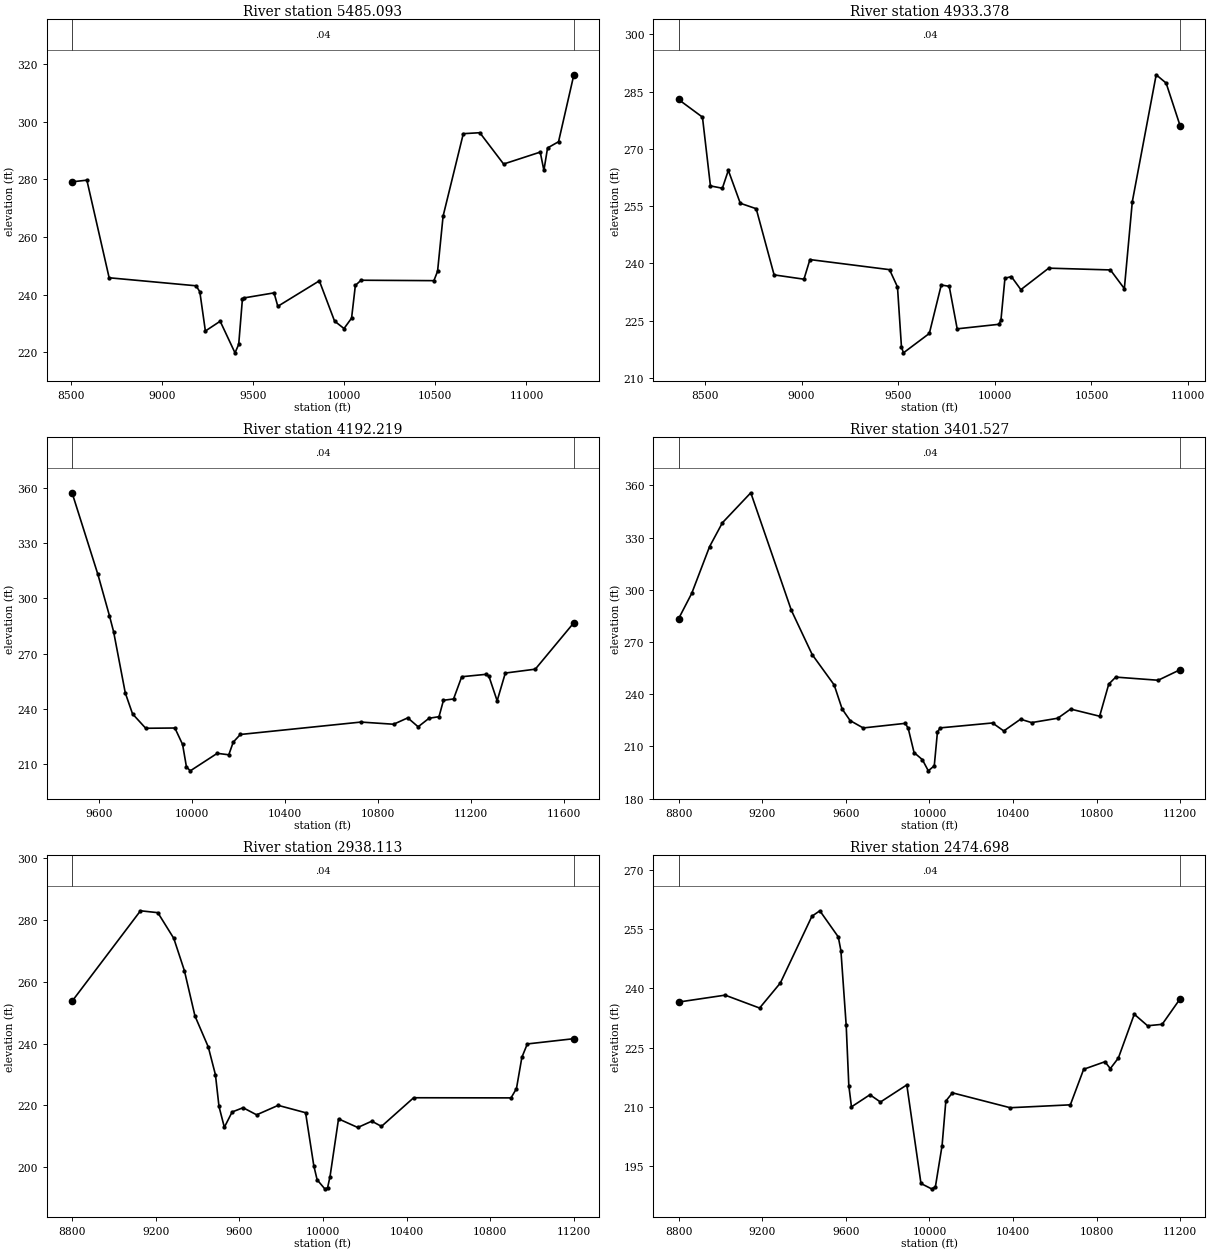
Type RM Length L Ch R = 1 ,5485.093,551.715500,551.715500,551.715500
XS GIS Cut Line= 6
723544.718040413729418.678151935 722473.38382413729616.603226716
721903.740976363729773.817341008721731.567748609729813.258396149
721454.753395519729854.897798858720841.352177703729916.272554069
#Sta/Elev= 30
8506.648279.11998587.886279.7018 8710.12245.82119187.445243.03739207.747240.9547
9238.199227.34219319.405230.73669400.701 219.7679421.104222.69449441.507238.4866
9451.708238.8443 9615.12240.58159635.728235.91489863.641244.76119947.063230.7941
9998.977228.1969 10040.5 231.81410061.27243.165810092.43244.967410492.25244.8223
10512.43248.0743 10542.7267.213610653.66295.835910744.19296.171910874.85285.2998
11075.79289.439811095.89283.100111115.98290.877811176.26 293.04511260.32316.2788
#Mann= 3 , 0 , 0
8506.648    0.04       08506.648    0.04       011260.32    0.04       0
#XS Ineff= 2 , 0
       09635.883        10096.79       0
Bank Sta=8506.648,11260.32
Exp/Cntr=0.3,0.1

Type RM Length L Ch R = 1 ,4933.378,741.159200,741.159200,741.159200
XS GIS Cut Line= 2
723555.240298897728795.420049667721033.700823128 729412.93992129
#Sta/Elev= 30
8363.585282.92598487.378278.3021 8528.56260.29388590.333259.6717 8621.22264.3616
8682.993255.74548765.357254.31548858.016236.98119012.449235.84979043.336240.9912
9455.156238.35019496.338233.81739516.929218.09489527.224216.55989661.066221.6375
9722.839234.33559764.021233.98059805.203222.849910021.41224.0375 10031.7225.2021
 10052.3236.088910085.46  236.5410134.66233.1101 10278.8238.743210597.96238.2773
10670.03233.381110711.21256.154310834.75289.399410886.23287.225110959.64275.8674
#Mann= 3 , 0 , 0
8363.585    0.04       08363.585    0.04       010959.64    0.04       0
#XS Ineff= 2 , 0
       09679.081         10173.9       0
Bank Sta=8363.585,10959.64
Exp/Cntr=0.3,0.1

Type RM Length L Ch R = 1 ,4192.219,790.691500,790.691500,790.691500
XS GIS Cut Line= 3
722397.390539646728177.900178045721582.607375681728795.420049667
720613.444243848 729387.20992662
#Sta/Elev= 30
 9483.26357.30729594.349313.02219644.017290.63279661.925281.96999712.115248.7753
9743.351237.41969799.948229.62259925.423229.76279958.576220.82889975.132208.6649
9991.688206.540410107.58216.035610157.25215.239510176.37222.113610206.91 226.254
10725.43232.982410866.03231.806610926.95235.265810971.48230.423311018.35 235.041
11061.27235.909611080.46244.8059 11123.8245.507711158.95 257.56611264.41258.8795
11276.12257.757111311.27244.499311346.42259.561911475.31261.666611641.17286.8445
#Mann= 3 , 0 , 0
 9483.26    0.04       0 9483.26    0.04       011641.17    0.04       0
#XS Ineff= 2 , 0
       09674.576        10620.71       0
Bank Sta=9483.26,11641.17
Exp/Cntr=0.3,0.1

Type RM Length L Ch R = 1 ,3401.527,463.414600,463.414600,463.414600
XS GIS Cut Line= 6
  722071.6139998727144.002823563   721744.934276727595.275109654
721534.967675483 727866.41805457721429.436374522727986.643794598
721085.387250161728344.140119772720534.616977364728985.856551076
#Sta/Elev= 30
8799.023283.33458862.128297.94338947.582324.82049008.972338.5195 9144.92355.7633
9339.131288.20049438.793262.78319544.035245.33199582.113231.53029620.505224.8377
9683.026 220.615 9884.67223.26549898.603220.30929926.468206.45859965.995 202.428
9994.718195.9682 10023.2198.869310038.31218.267910051.63220.656810301.94223.4815
10355.89218.881610436.14225.637610489.26223.6924 10614.2226.204310675.88231.4679
10814.72227.351710858.41245.819210891.85249.8369 11094.8248.030711200.98254.1415
#Mann= 3 , 0 , 0
8799.023    0.04       08799.023    0.04       011200.98    0.04       0
#XS Ineff= 2 , 0
       0                 10531.8       0
Bank Sta=8799.023,11200.98
Exp/Cntr=0.3,0.1

Type RM Length L Ch R = 1 ,2938.113,463.414600,463.414600,463.414600
XS GIS Cut Line= 6
721730.468043903726835.599435912721478.020561051727173.897219734
721220.575480147727499.363404807721055.757995823727697.553642098
 720578.79372036728256.002408168720212.520996204728696.258269552
#Sta/Elev= 30
8799.011253.7111 9126.52282.9718 9209.54282.35979285.872274.0535 9336.55263.6436
9387.227 248.9529451.009238.93339485.261229.94949502.298 219.6889527.943212.9448
9565.143217.9002  9617.7219.27759682.467216.97899785.594220.04079916.817217.6617
9956.249200.48599972.097195.965910008.78193.042610021.94193.342710033.77196.9958
10074.55215.669410166.62 212.88210233.89214.926410280.07213.237510434.01222.5027
10900.17222.457610926.18225.4506 10952.2 235.58810978.22239.906411200.99241.6044
#Mann= 3 , 0 , 0
8799.011    0.04       08799.011    0.04       011200.99    0.04       0
#XS Ineff= 2 , 0
       0                10547.13       0
Bank Sta=8799.011,11200.99
Exp/Cntr=0.3,0.1

Type RM Length L Ch R = 1 ,2474.698,463.414700,463.414700,463.414700
XS GIS Cut Line= 6
 721359.83573323726527.471157324721104.360828439726863.502137811
720694.095309552727396.693975164720546.253172149727594.566091569
720245.488718255727979.614367889719891.123088847728427.984506401
#Sta/Elev= 30
8799.009236.55099022.019238.30599187.026235.03449286.106241.36869437.518258.3137
9475.371 259.6999563.695253.07239576.312249.55839601.548230.64649614.165215.3531
9626.783209.97799715.107213.04539765.577211.20399891.754215.54339959.509190.5449
10010.05189.1876 10028.5189.686510060.61200.173310078.53211.447310110.03213.5333
10386.62209.7567 10674.6210.492210738.33219.5091 10840.3221.422310865.79219.6722
10904.45222.363310980.51 233.47411044.24230.540511114.11230.9091   11201237.4496
#Mann= 3 , 0 , 0
8799.009    0.04       08799.009    0.04       0   11201    0.04       0
#XS Ineff= 2 , 0
       0                10655.02       0
Bank Sta=8799.009,11201
Exp/Cntr=0.3,0.1

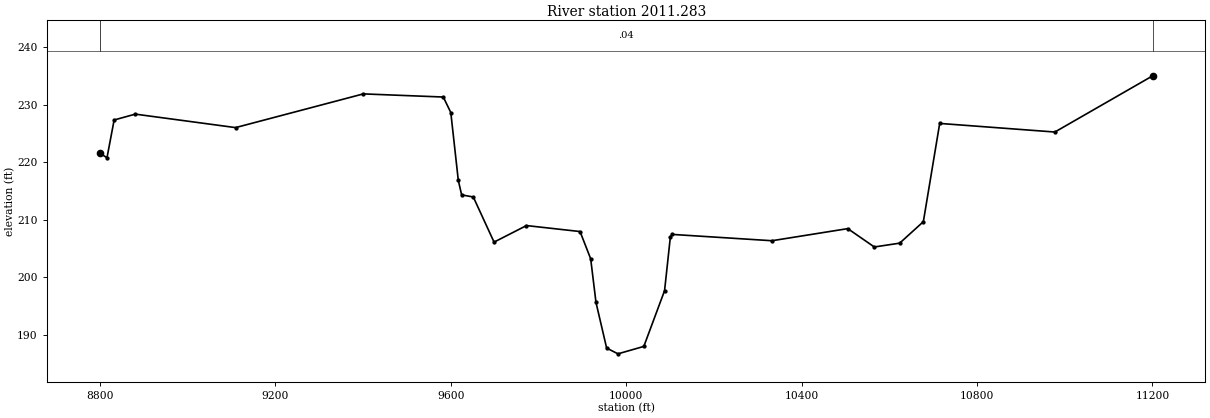
Type RM Length L Ch R = 1 ,2011.283,0.000000,0.000000,0.000000
XS GIS Cut Line= 6
720975.525454928 726251.87412058 720713.61607389 726582.91478095
720508.389931557726852.455527798720350.709530444727071.378435812
719954.339725293 727641.09571395719547.783964203728182.665605538
#Sta/Elev= 30
8799.016221.64688815.753220.76438832.097227.35648880.447228.37289109.032226.0273
9400.507 231.896 9582.83231.3495 9599.94228.65699617.051216.85039624.674214.3142
9651.271213.95019698.617206.0923 9772.56208.97379894.742207.93339918.995203.1861
9931.122195.58639955.376187.65069981.231 186.644 10040.2187.936910087.53197.6454
10100.77 207.03110105.25207.432610332.43 206.33410505.34208.441610565.91205.2453
10623.74205.911710677.74209.647410715.02226.755610977.69225.256611200.98235.0494
#Mann= 3 , 0 , 0
8799.016    0.04       08799.016    0.04       011200.98    0.04       0
#XS Ineff= 2 , 0
       0                               0
Bank Sta=8799.016,11200.98
Exp/Cntr=0.3,0.1